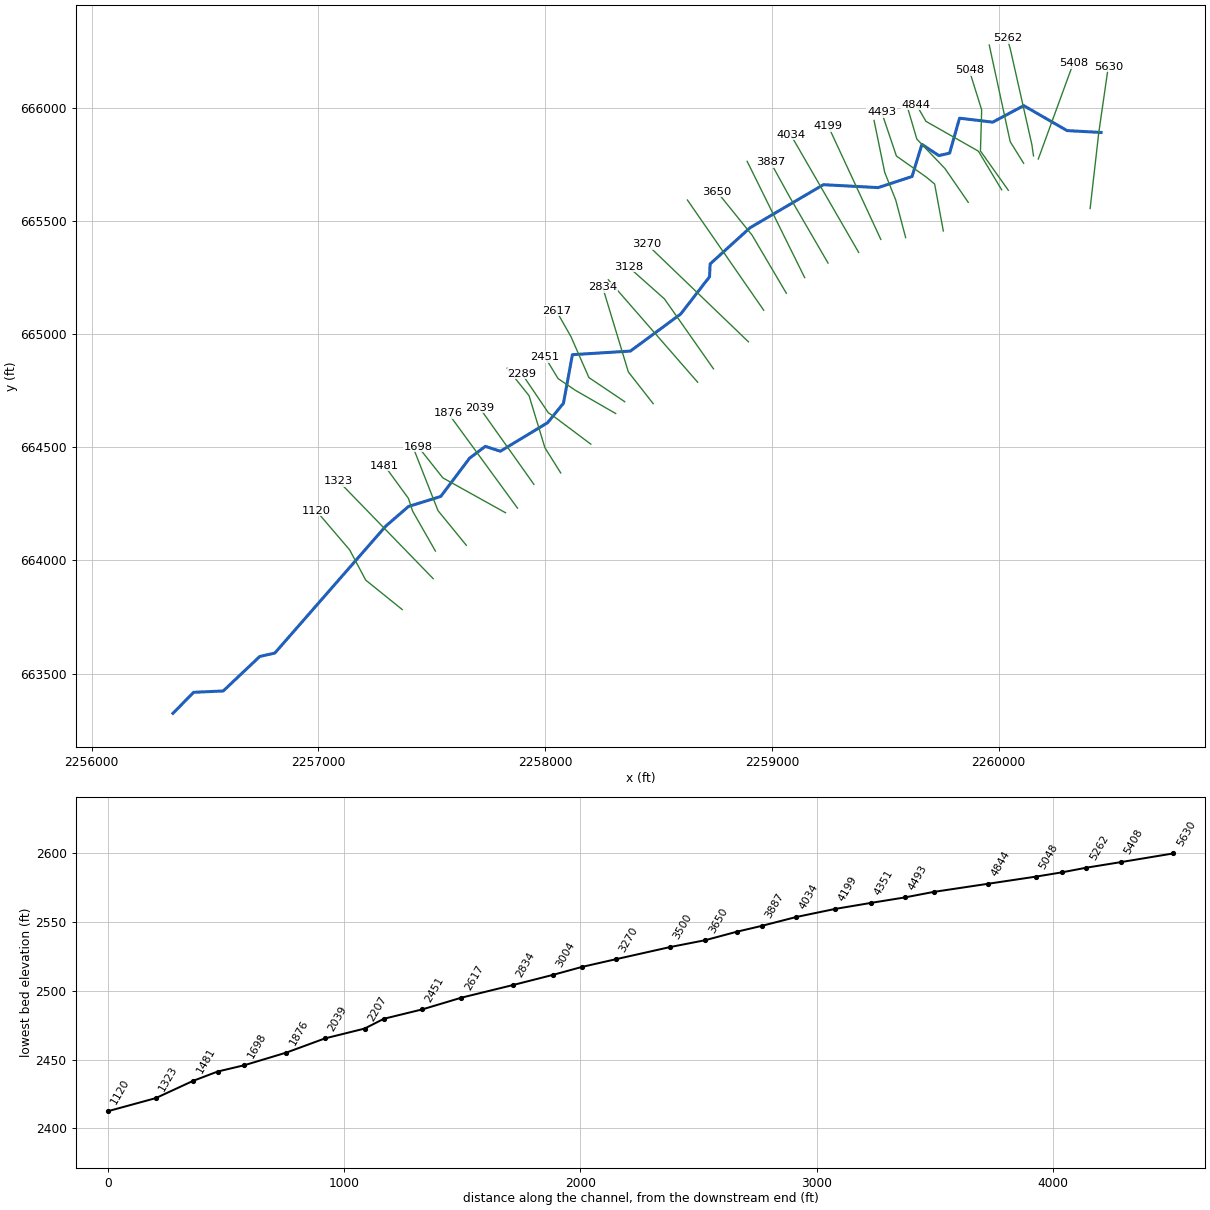
--- PNTHRNT1_1.prj (project) ---

Proj Title=PNTHRNT1_1
Current Plan=p01
Default Exp/Contr=0,0
English Units
Geom File=g01
Flow File=f01
Plan File=p01
BEGIN DESCRIPTION:
----------MODEL BY WOOD PLC 2022----------
AFH study:PNTHRNT1_1
Randolph County, WV
HEC-RAS Version: RAS 6.2
Vertical Datum: NAVD88
Projection: NAD 1983 StatePlane West Virginia S FIPS 4702 (US Feet)
Terrain: 1-meter LIDAR (FEMA Region III 3DEP collected 2016-2018)
Land Use: 2019 NLCD
Hydrologic Method:
WV SIR2010-5033 regression equations
Additional Model Notes:
None
END DESCRIPTION:
DSS Export Rating Curves= 0
DSS Export Rating Curve Sorted= 0
DSS Export Volume Flow Curves= 0
DXF OffsetX= 0
DXF OffsetY= 0
DXF ScaleX= 0
DXF ScaleY= 0

--- PNTHRNT1_1.p01 (plan) ---

Plan Title=Floodplain
Program Version=6.20
Short Identifier=Floodplain
Geom File=g01
Flow File=f01
Subcritical Flow
K Sum by GR= 0
Std Step Tol= 0.01
Critical Tol= 0.01
Num of Std Step Trials= 20
Max Error Tol= 0.3
Flow Tol Ratio= 0.001
Split Flow NTrial= 30
Split Flow Tol= 0.02
Split Flow Ratio= 0.02
Log Output Level= 0
Friction Slope Method= 1
Unsteady Friction Slope Method= 2
Unsteady Bridges Friction Slope Method= 1
Parabolic Critical Depth
Global Vel Dist= 0 , 0 , 0
Global Log Level= 0
CheckData=True
Encroach Param=-1 ,0,0, 0
Mapping Interval=1HOUR
Computation Time Step Use Courant=        0
Computation Time Step Use Time Series=    0
Computation Time Step Count To Double=0
Computation Time Step Max Doubling=0
Computation Time Step Max Halving=0
Computation Time Step Residence Courant=0
Run HTab= 0
Run UNet= 0
Run Sediment= 0
Run PostProcess= 0
Run WQNet= 0
Run RASMapper=-1
UNET Theta= 0
UNET Theta Warmup= 0
UNET ZTol= 0
UNET ZSATol= 0
UNET MxIter= 0
UNET Max Iter WO Improvement= 0
UNET MaxInSteps= 0
UNET DtIC= 0
UNET DtMin= 0
UNET MaxCRTS= 0
UNET WFStab= 0
UNET SFStab= 0
UNET WFX= 1
UNET SFX= 1
UNET Gravity=32.174
UNET 1D Methodology=Finite Difference
UNET DSS MLevel= 1
UNET Pardiso=0
UNET DZMax Abort= 0
UNET Use Existing IB Tables= 0
UNET Froude Reduction=False
UNET Froude Limit= 0
UNET Froude Power= 0
UNET D1 Cores= 0
UNET WindReference=Eulerian
UNET WindDragFormulation=Hsu (1988)
UNET D2 Coriolis=0
UNET D2 Cores= 0
UNET D2 Theta= 1
UNET D2 Theta Warmup= 1
UNET D2 Z Tol= 0.01
UNET D2 Volume Tol= 0.01
UNET D2 Max Iterations= 20
UNET D2 Equation= 0
UNET D2 RampUpFraction=0.1
UNET D2 TimeSlices= 1
UNET D2 Turbulence Formulation=Non-Conservative (original)
UNET D2 Eddy Viscosity=0.3
UNET D2 Transverse Eddy Viscosity=0.1
UNET D2 Smagorinsky Mixing=0
UNET D2 BCVolumeCheck=0
UNET D2 Cores=0
UNET D2 SolverType=PARDISO (Direct)
UNET D2 Minimum Iterations= 2147483647
UNET D2 Maximum Iterations= 2147483647
UNET D2 Restart Number= 10
UNET D2 Relaxation Coeff=1.3
UNET D2 SOR Precondition Iterations= 10
UNET D2 ILUT Maximum Fill= 8
UNET D2 ILUT Tolerance=1E-08
UNET D1D2 MaxIter= 0
UNET D1D2 ZTol=0.01
UNET D1D2 QTol=0.1
UNET D1D2 MinQTol=1
Write IC File= 0
Write IC File at Fixed DateTime=0
Write IC File at Sim End=0
Echo Input=False
Echo Parameters=False
Echo Output=False
Write Detailed= 0
HDF Write Warmup=0
HDF Write Time Slices=0
HDF Flush=0
HDF Compression= 1
HDF Chunk Size= 1
HDF Spatial Parts= 1
HDF Use Max Rows=0
HDF Fixed Rows= 1
Calibration Method= 0
Calibration Iterations= 20
Calibration Max Change=0.05
Calibration Tolerance=0.2
Calibration Maximum=1.5
Calibration Minimum=0.5
Calibration Optimization Method= 1
WQ AD Non Conservative
WQ ULTIMATE=-1
WQ Max Comp Step=1HOUR
WQ Output Interval=15MIN
WQ Output Selected Increments= 0
WQ Output face flow=0
WQ Output face velocity=0
WQ Output face area=0
WQ Output face dispersion=0
WQ Output cell volume=0
WQ Output cell surface area=0
WQ Output cell continuity=0
WQ Output cumulative cell continuity=0
WQ Output face conc=0
WQ Output face dconc_dx=0
WQ Output face courant=0
WQ Output face peclet=0
WQ Output face adv mass=0
WQ Output face disp mass=0
WQ Output cell mass=0
WQ Output cell source sink temp=0
WQ Output nsm pathways=0
WQ Output nsm derived pathways=0
WQ Create Restart=0
WQ Fixed Restart=0
WQ System Summary=0
WQ Write To DSS=0
Sorting and Armoring Iterations= 10
XS Update Threshold= 0.02
Bed Roughness Predictor= 0
Hydraulics Update Threshold= 0.02
Energy Slope Method= 1
Volume Change Method= 1
Sediment Retention Method= 0
Sediment TS Multiplier= 1
Warm Up Method= 0
XS Weighting Method= 0
Number of US Weighted Cross Sections= 1
Number of DS Weighted Cross Sections= 1
Upstream XS Weight=0
Main XS Weight=1
Downstream XS Weight=0
Number of DS XS's Weighted with US Boundary= 1
Upstream Boundary Weight= 1
Weight of XSs Associated with US Boundary= 0
Number of US XS's Weighted with DS Boundary= 1
Downstream Boundary Weight= 0.5
Weight of XSs Associated with DS Boundary= 0.5
Percentile Method= 0
Sediment Output Level= 3
Mass or Volume Output= 0
Output Increment Type= 1
Profile and TS Output Increment= 1
Transport Output Increment 1
XS Output Flag= 0
XS Output Increment= 10
Read HDF5 Sediment Hotstart= 0
Sediment Hotstart Type= 0
Write Gradation File= 0
Read Gradation Hotstart= 0
Write HDF5 File= 1
Write Binary Output= 1
Write DSS Sediment File= 0
DSS Sediment Output Type= 1
SV Curve= 0
Specific Gage Flag= 0
Subcell Erosion Methods= 0
Subcell Deposition Methods= 0
Advection Scheme= 1
Matrix Solver= 0
Implicit Weighting Factor= 1
Maximum Outer Loop Convergence Iterations= 5
Convergence Maximum Absolute= 0.001
Convergence RMSE= 0.0001
Grain Fractions Max Abs Error= 0.001
Max Subgrid Regions= 1
Max Subgrid Length Scale= 3.402823E+38
Initial Layer Thickness= 3.402823E+38
Min Layer Thickness= 3.402823E+38
Max Layer Thickness= 3.402823E+38
Number of Layers= 5

--- PNTHRNT1_1.f01 (steady flow) ---

Flow Title=Flow
Program Version=6.20
Number of Profiles= 1
Profile Names=P100yr
River Rch & RM=PNTHRNT1_1,Main            ,5630
     386
Boundary for River Rch & Prof#=PNTHRNT1_1,Main            , 1
Up Type= 0
Dn Type= 3
Dn Slope=0.04056
DSS Import GetInterval= 0
DSS Import GetPeak= 0
DSS Import FillOption= 0

--- PNTHRNT1_1.g01 (geometry) ---

Geom Title=Geometry
Program Version=6.20

River Reach=PNTHRNT1_1      ,Main
Reach XY= 30
     2260451.723665890.5869999982260301.98299998665898.702999994
2260110.90300003 666008.990000012259974.15200001665936.082000017
2259827.75400001665953.6899999982259784.00400002665799.175999999
2259736.60800003      665788.4122259661.78100003665837.717999995
2259618.32100001 665695.907000022259468.84200004665646.947999999
2259227.52200001665659.795000002     2258903.737665469.447999999
     2258727.869665309.552000016     2258725.265665252.954999998
2258598.35500002 665088.615000012258376.48100004664924.725999996
2258120.57799999664908.7539999932258081.09900004664694.274000019
2258011.13300003664608.1630000172257802.79999998664482.199926477
     2257736.654664503.6490000192257667.90400003664452.347000018
2257539.77899998664282.3819999992257397.41800003664237.937999994
     2257297.765664151.4800000192256808.18199998663590.368000001
     2256741.862663575.438000008     2256580.751663423.006999999
2256450.19600002663417.104000002     2256358.978      663324.017

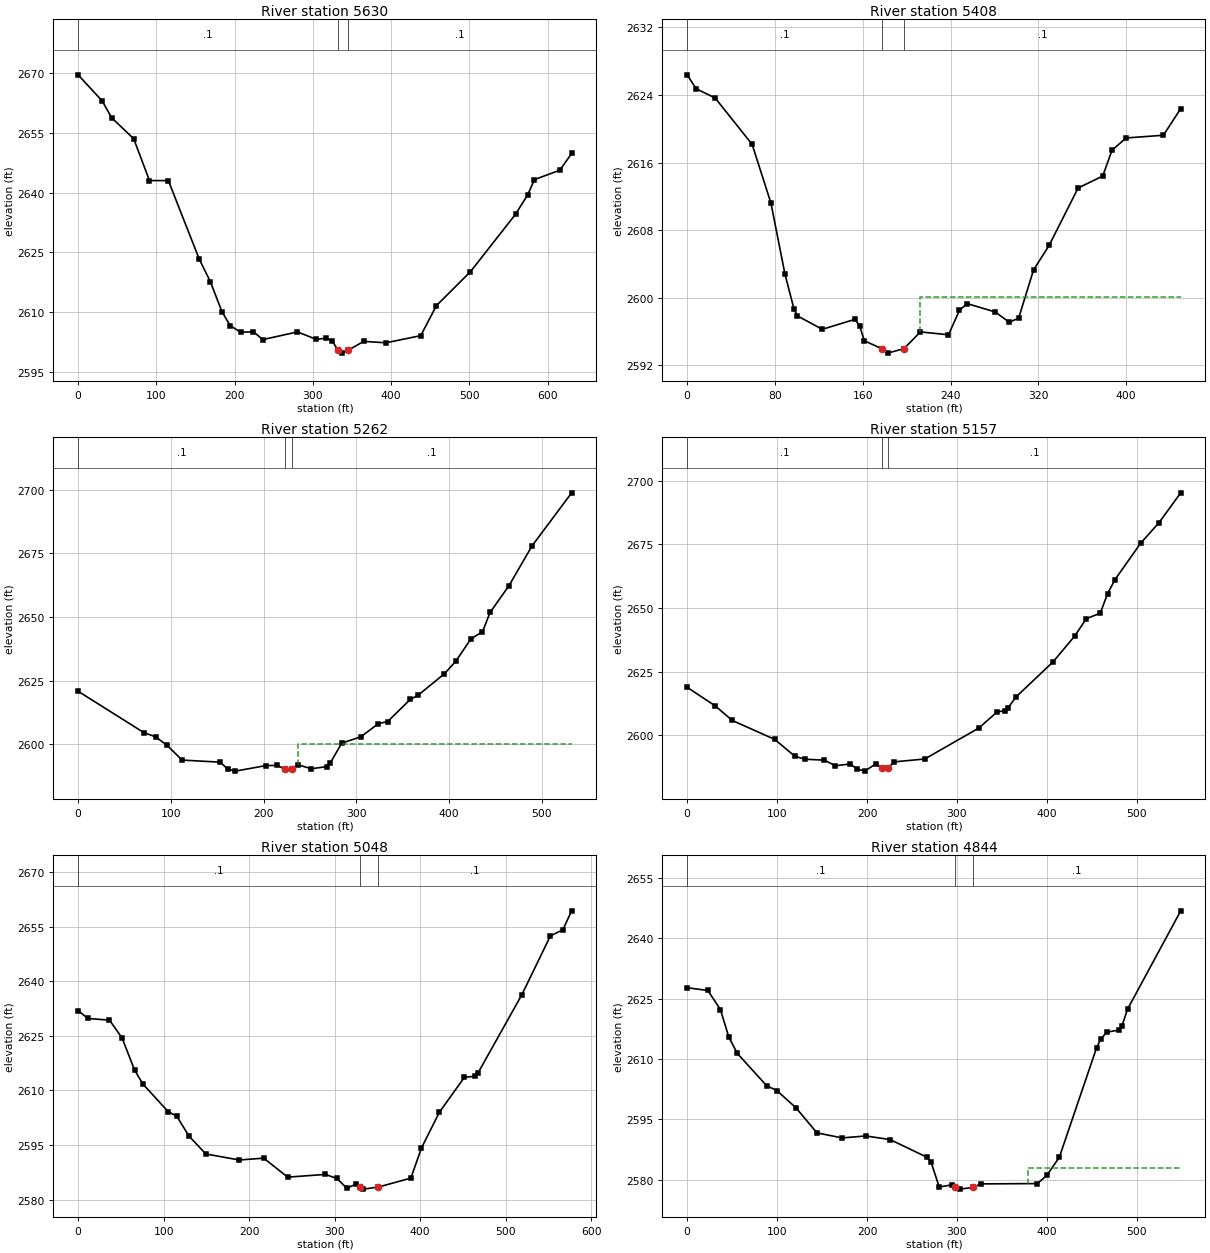
Type RM Length L Ch R = 1 ,5630    ,222.9,221.7,219.2
XS GIS Cut Line= 3
2260403.64015459665554.546072677     2260441.773      665889.585
2260483.63244732666180.182777748
#Sta/Elev= 30
       0 2669.49    30.8 2662.94    42.9 2658.73    71.1 2653.47    91.2 2642.99
   115.4 2642.98   154.7 2623.36   169.1 2617.63   183.8 2610.16   194.4 2606.63
     208 2604.98   224.1 2605.11   236.1 2603.14   280.4 2605.07   304.6 2603.18
   317.3 2603.52   324.7 2602.85  332.032600.501   336.8 2599.75  345.372600.499
   365.1  2602.7   393.4 2602.34   437.9 2604.13     458 2611.66   501.5 2620.17
   559.1 2634.56   574.7 2639.46   583.3 2643.24   615.6 2645.58   630.8 2649.78
#Mann= 3 ,-1,0
       0      .1       0  332.03    .045       0  345.37      .1       0
Bank Sta=332.03,345.37
XS Rating Curve= 0 ,0
Exp/Cntr=0.3,0.1

Type RM Length L Ch R = 1 ,5408    ,144.6,146.3,147.4
XS GIS Cut Line= 2
2260175.12067601665773.5224982842260329.28172876666196.003683573
#Sta/Elev= 30
       0 2626.38     8.2 2624.73    25.5 2623.64    59.2 2618.15    76.3 2611.21
    89.1  2602.8    97.3 2598.68   100.4 2597.86   123.1 2596.27   152.9 2597.45
   157.2 2596.66   161.4 2594.91  177.262593.983   182.7 2593.45  197.562593.983
   212.5 2595.96   238.1 2595.62   248.1 2598.52   255.1 2599.31   280.7 2598.32
   293.4 2597.11     302 2597.58   315.6  2603.3   329.8  2606.2   356.2 2612.99
   378.6  2614.4   387.1 2617.46   399.9 2618.91   433.9 2619.23   449.7 2622.39
#Mann= 3 ,-1,0
       0      .1       0  177.26    .045       0  197.56      .1       0
#XS Ineff= 2 , 0
                          212.55         2600.05
Permanent Ineff=
       F       F
Bank Sta=177.26,197.56
XS Rating Curve= 0 ,0
Exp/Cntr(USF)=0,0
Exp/Cntr=0.3,0.1

Type RM Length L Ch R = 1 ,5262    ,104.5,104.7,104.6
XS GIS Cut Line= 4
2260153.94241485665787.0349931312260146.66575028665837.062062097
2260052.06911078666257.289441413 2260038.4253647666306.406927307
#Sta/Elev= 30
       0 2620.79    71.2 2604.47    83.5  2602.9    95.8 2599.58   112.2 2593.73
     153 2592.92   161.4 2590.24   169.6 2589.39   202.4 2591.56   214.7 2591.65
   222.9 2590.18  230.162590.183   236.8 2591.91   251.6 2590.32     268 2591.16
   272.1 2592.69   284.4 2600.41   304.9 2602.88   323.8 2608.04   333.9 2608.89
   358.2 2617.57   366.4 2619.15   395.1 2627.67   407.4 2632.61   423.8 2641.45
   436.1 2644.15   444.3 2651.75   464.8 2662.35   489.5  2677.9   532.3 2698.79
#Mann= 3 ,-1,0
       0      .1       0   222.9    .045       0  230.16      .1       0
#XS Ineff= 2 , 0
                          237.08          2599.9
Permanent Ineff=
       F       F
Bank Sta=222.9,230.16
XS Rating Curve= 0 ,0
Exp/Cntr(USF)=0,0
Exp/Cntr=0.3,0.1

Type RM Length L Ch R = 1 ,5157    ,111.7,108.8,106.7
XS GIS Cut Line= 3
2260110.41416602665754.5013354682260051.13620899665849.935010493
2259958.84062942666276.643411891
#Sta/Elev= 30
       0 2618.89    31.4 2611.55    50.2 2605.86    97.3 2598.44   119.8 2591.81
     131 2590.64   152.5 2590.29   164.8 2588.09   181.1 2588.77   189.3 2586.79
   197.5 2585.97   209.8 2588.83  216.19  2587.1  223.13 2587.13   230.3 2589.61
   264.2 2590.73   324.4  2602.9   344.8 2609.26     353 2609.65   356.5  2610.6
   365.3 2614.97   406.9 2628.89   430.8 2638.94   443.9 2645.83   459.4 2648.02
   467.6 2655.73   475.8  2661.2   504.5 2675.58   524.7 2683.54   548.9 2695.28
#Mann= 3 ,-1,0
       0      .1       0  216.19    .045       0  223.13      .1       0
Bank Sta=216.19,223.13
XS Rating Curve= 0 ,0
Exp/Cntr=0.3,0.1

Type RM Length L Ch R = 1 ,5048    ,188.7,204.1,212
XS GIS Cut Line= 4
2260042.82457718665635.2114848242259919.99899542665808.713675569
2259925.42926975665990.1105194912259870.90905504666164.873753062
#Sta/Elev= 30
       0 2631.92    11.5 2629.77    36.7 2629.32    51.4 2624.43    66.1 2615.57
    75.9 2611.72   105.3  2604.2   115.4 2602.93   129.6 2597.48   149.4 2592.55
   188.6  2590.9     217 2591.41   245.1 2586.19   289.1 2586.94   302.6 2585.83
   314.2 2583.15   325.1 2584.29   329.8 2583.49   333.7  2582.9  351.21 2583.48
   389.1 2585.93   401.5  2594.2   422.4 2604.01   451.7 2613.61   464.3 2613.91
   467.8 2614.89   518.9 2636.31   552.3 2652.48   566.8 2654.13   577.1 2659.34
#Mann= 3 ,-1,0
       0      .1       0   329.8    .045       0  351.21      .1       0
Bank Sta=329.8,351.21
XS Rating Curve= 0 ,0
Exp/Cntr(USF)=0,0
Exp/Cntr=0.3,0.1

Type RM Length L Ch R = 1 ,4844    ,232.8,229.8,220.1
XS GIS Cut Line= 4
2260013.34688611665637.4453858542259911.11709964665807.828363298
2259679.94884376665939.5297999172259637.58334666666012.287936231
#Sta/Elev= 30
       0 2627.74      23 2627.06      37 2622.31    46.3 2615.48    55.7 2611.42
    88.3  2603.4    99.8 2602.16     121 2597.89   144.3 2591.66   172.3  2590.4
   198.7 2590.89   225.7 2589.99   266.5 2585.62   271.1 2584.47   280.3 2578.19
   294.2 2578.73  298.05  2578.1   303.4 2577.67  318.122578.107   326.4 2578.97
   389.5 2579.05     400  2581.1   413.9  2585.6   455.3  2612.8     460 2614.99
   466.7  2616.7   480.4 2617.22   483.3 2618.13   489.8 2622.44   548.9 2646.86
#Mann= 3 ,-1,0
       0      .1       0  298.05    .045       0  318.12      .1       0
#XS Ineff= 2 , 0
                           379.4         2582.84
Permanent Ineff=
       F       F
Bank Sta=298.05,318.12
XS Rating Curve= 0 ,0
Exp/Cntr(USF)=0,0
Exp/Cntr=0.3,0.1

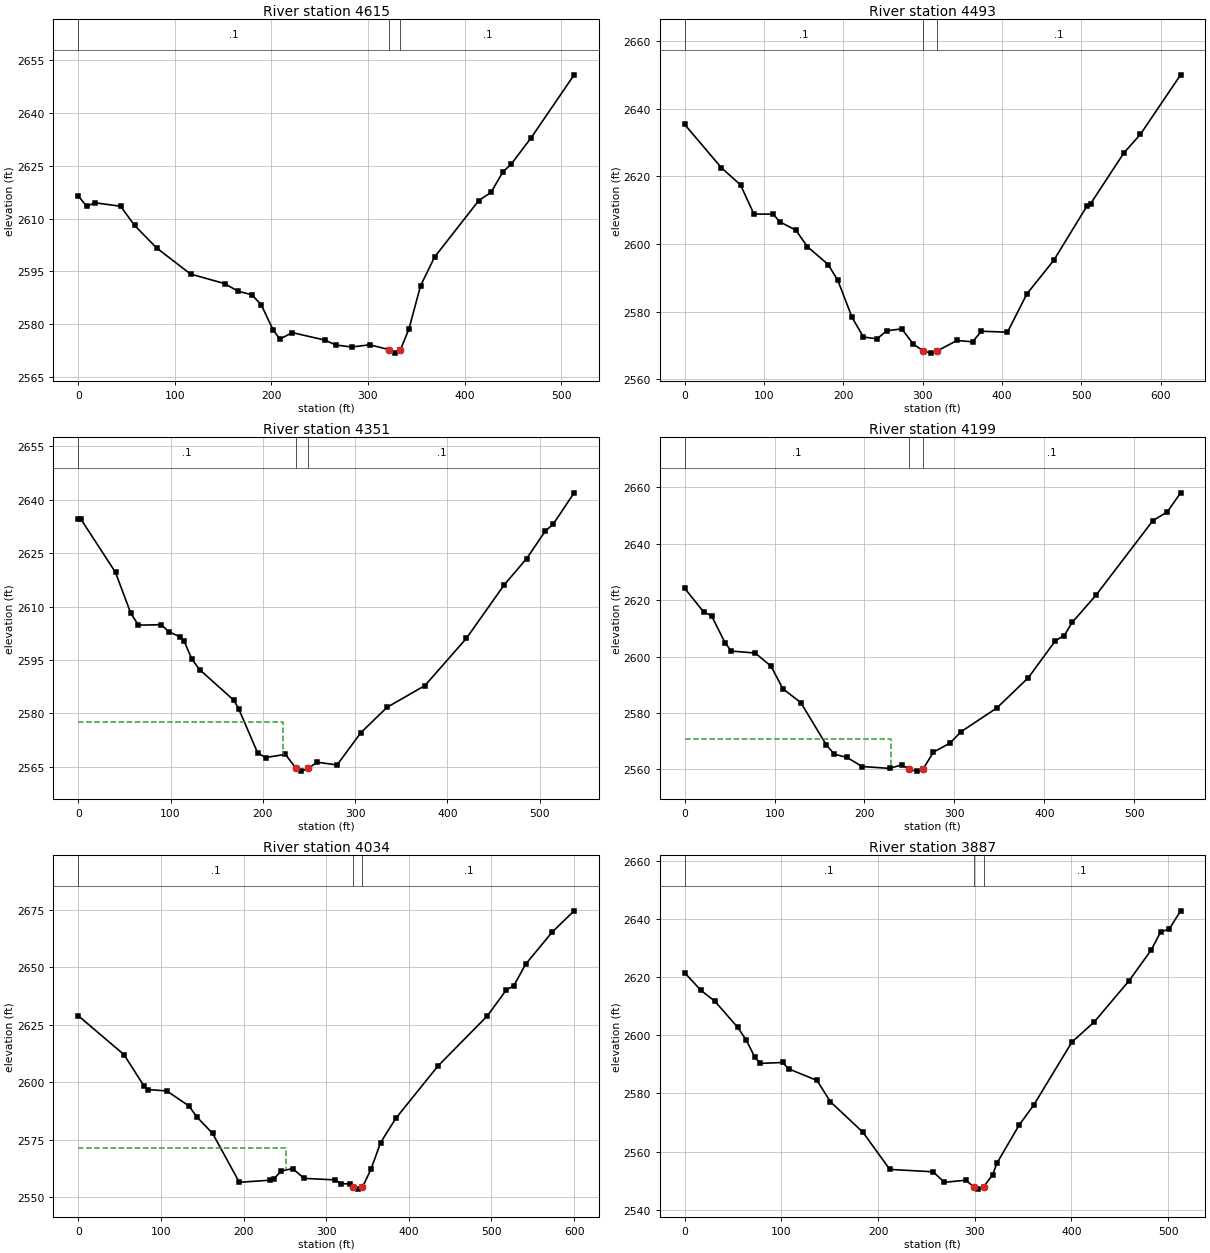
Type RM Length L Ch R = 1 ,4615    ,121.3,122.3,120.9
XS GIS Cut Line= 4
2259866.16050029665582.0626921652259763.55672391665730.940575948
2259639.39309018665861.4022973412259596.42351436666007.862125485
#Sta/Elev= 30
       0 2616.49     8.6 2613.53    17.6 2614.48    43.9 2613.51    58.3 2608.08
    81.3 2601.63   116.3 2594.24   151.5 2591.53   165.6 2589.34   179.7 2588.35
   189.4 2585.57   201.8 2578.33   208.9 2575.76   221.6 2577.59   255.3 2575.47
   266.9 2574.06   283.3  2573.5   301.8 2574.13   321.9 2572.75   327.5 2571.76
  333.682572.752   342.4  2578.6   354.5 2590.92     369 2599.08   414.8 2615.14
   427.4 2617.44   439.9 2623.35   448.2 2625.42   469.1 2633.02   513.5 2650.86
#Mann= 3 ,-1,0
       0      .1       0   321.9    .045       0  333.68      .1       0
Bank Sta=321.9,333.68
XS Rating Curve= 0 ,0
Exp/Cntr(USF)=0,0
Exp/Cntr=0.3,0.1

Type RM Length L Ch R = 1 ,4493    ,146.4,141.8,136.3
XS GIS Cut Line= 5
2259756.27211992665455.3251929412259717.96687498665662.855941689
2259680.31013579665693.9636827562259549.33017341665786.468281189
2259484.02144564665980.828130247
#Sta/Elev= 30
       0 2635.37    46.3 2622.58    70.4 2617.51    87.3 2608.88   111.7 2608.85
   119.8  2606.6   140.2 2604.12   154.8 2599.22   180.9 2593.96   193.1 2589.27
     211 2578.33   225.3 2572.53   242.4 2571.97   254.9 2574.36   273.8 2574.92
   288.1 2570.44  300.822568.398   311.1 2567.75  318.342568.398   343.3 2571.49
   362.9 2571.09   374.2 2574.22     407 2573.95   431.5 2585.28   465.3 2595.18
   507.5 2611.35   511.8 2611.93   553.9 2627.01   574.6 2632.46   625.3 2650.06
#Mann= 3 ,-1,0
       0      .1       0  300.82    .045       0  318.34      .1       0
Bank Sta=300.82,318.34
XS Rating Curve= 0 ,0
Exp/Cntr(USF)=0,0
Exp/Cntr=0.3,0.1

Type RM Length L Ch R = 1 ,4351    ,151.2,152.2,152.8
XS GIS Cut Line= 4
2259590.10848922665426.1500689212259546.54373511665591.458268204
2259497.83269927665714.1694971322259450.76211517 665943.63306752
#Sta/Elev= 30
       0 2634.62     3.1 2634.44    40.4 2619.57    56.9 2608.12    65.2 2604.78
      90  2604.9    98.3  2602.9   110.7 2601.46   114.8 2600.24   123.1 2595.25
   131.4 2592.32   168.6  2583.7   174.1 2581.16   194.3 2568.97   202.9 2567.63
   224.4 2568.52  235.852564.635   241.7 2563.82  249.372564.635   258.9 2566.32
   280.4 2565.55   306.1 2574.59   334.6 2581.74   375.5 2587.81   420.4 2601.05
   461.2    2616   485.7 2623.45   506.1 2631.22   514.3 2633.03   537.2  2641.9
#Mann= 3 ,-1,0
       0      .1       0  235.85    .045       0  249.37      .1       0
#XS Ineff= 2 , 0
          221.82 2577.71
Permanent Ineff=
       F       F
Bank Sta=235.85,249.37
XS Rating Curve= 0 ,0
Exp/Cntr(USF)=0,0
Exp/Cntr=0.3,0.1

Type RM Length L Ch R = 1 ,4199    ,164.1,164.3,162.6
XS GIS Cut Line= 2
 2259480.6018795665418.0839828972259248.75810273665918.625919321
#Sta/Elev= 30
       0 2624.23      21 2615.87    29.9 2614.49    44.8 2604.98    51.9 2601.98
    78.4 2601.28      96 2596.64   109.2 2588.61   129.2 2583.69   157.7 2568.62
   166.5  2565.4   180.4  2564.3   197.4 2561.05   228.2 2560.39   241.5 2561.68
   249.7 2560.05   258.7 2559.42   264.92560.049   276.7 2566.17   294.9 2569.31
   307.6 2573.44   347.3 2581.83   382.3 2592.57   412.4 2605.69   422.2 2607.49
     431 2612.13   457.5  2621.8   520.8 2648.24   536.8 2651.31   551.6 2658.07
#Mann= 3 ,-1,0
       0      .1       0   249.7    .045       0   264.9      .1       0
#XS Ineff= 2 , 0
          229.62 2570.75
Permanent Ineff=
       F       F
Bank Sta=249.7,264.9
XS Rating Curve= 0 ,0
Exp/Cntr(USF)=0,0
Exp/Cntr=0.3,0.1

Type RM Length L Ch R = 1 ,4034    ,147,147.4,147.1
XS GIS Cut Line= 2
2259383.07739631665360.315255307 2259083.4667748665880.155110914
#Sta/Elev= 30
       0  2628.9    55.5 2611.95    79.5 2598.37    84.1 2596.83   107.2 2596.21
     134 2589.68   143.3    2585   162.6 2577.77   194.9 2556.54   231.8 2557.44
   236.5 2557.97   245.8 2561.49   259.5 2562.46   273.4 2558.24   310.3 2557.59
   318.2    2556   328.8 2555.73  332.96 2554.31     338 2553.57  343.762554.313
   354.1 2562.11   365.9 2573.82   384.2 2584.29     435 2606.95   494.8 2628.75
   518.1 2640.16     527 2641.89   541.2  2651.2   573.5 2665.24     600 2674.44
#Mann= 3 ,-1,0
       0      .1       0  332.96    .045       0  343.76      .1       0
#XS Ineff= 2 , 0
          251.33 2571.56
Permanent Ineff=
       F       F
Bank Sta=332.96,343.76
XS Rating Curve= 0 ,0
Exp/Cntr(USF)=0,0
Exp/Cntr=0.3,0.1

Type RM Length L Ch R = 1 ,3887    ,105.5,104.9,103.8
XS GIS Cut Line= 3
2259247.73988542665313.6175124822259077.95104529665606.705391277
2258994.06727308665759.313217821
#Sta/Elev= 30
       0 2621.45    16.9 2615.38    31.1 2611.71    54.9 2602.67    63.8 2598.24
    72.5 2592.45    78.1 2590.29   101.2 2590.61   107.7 2588.39   136.9 2584.43
   150.7 2577.11   184.4 2566.61   212.1 2553.85   256.9 2553.03   268.6 2549.42
   290.7 2550.13   298.72547.946   303.8 2547.07  309.392547.948   318.5 2552.05
   323.1  2556.1   346.1  2569.2   360.8 2575.88   400.5 2597.63   423.7  2604.6
   459.7 2618.76   482.4 2629.24   492.2 2635.46   501.3 2636.56   512.9 2642.75
#Mann= 3 ,-1,0
       0      .1       0   298.7    .045       0  309.39      .1       0
Bank Sta=298.7,309.39
XS Rating Curve= 0 ,0
Exp/Cntr(USF)=0,0
Exp/Cntr=0.3,0.1

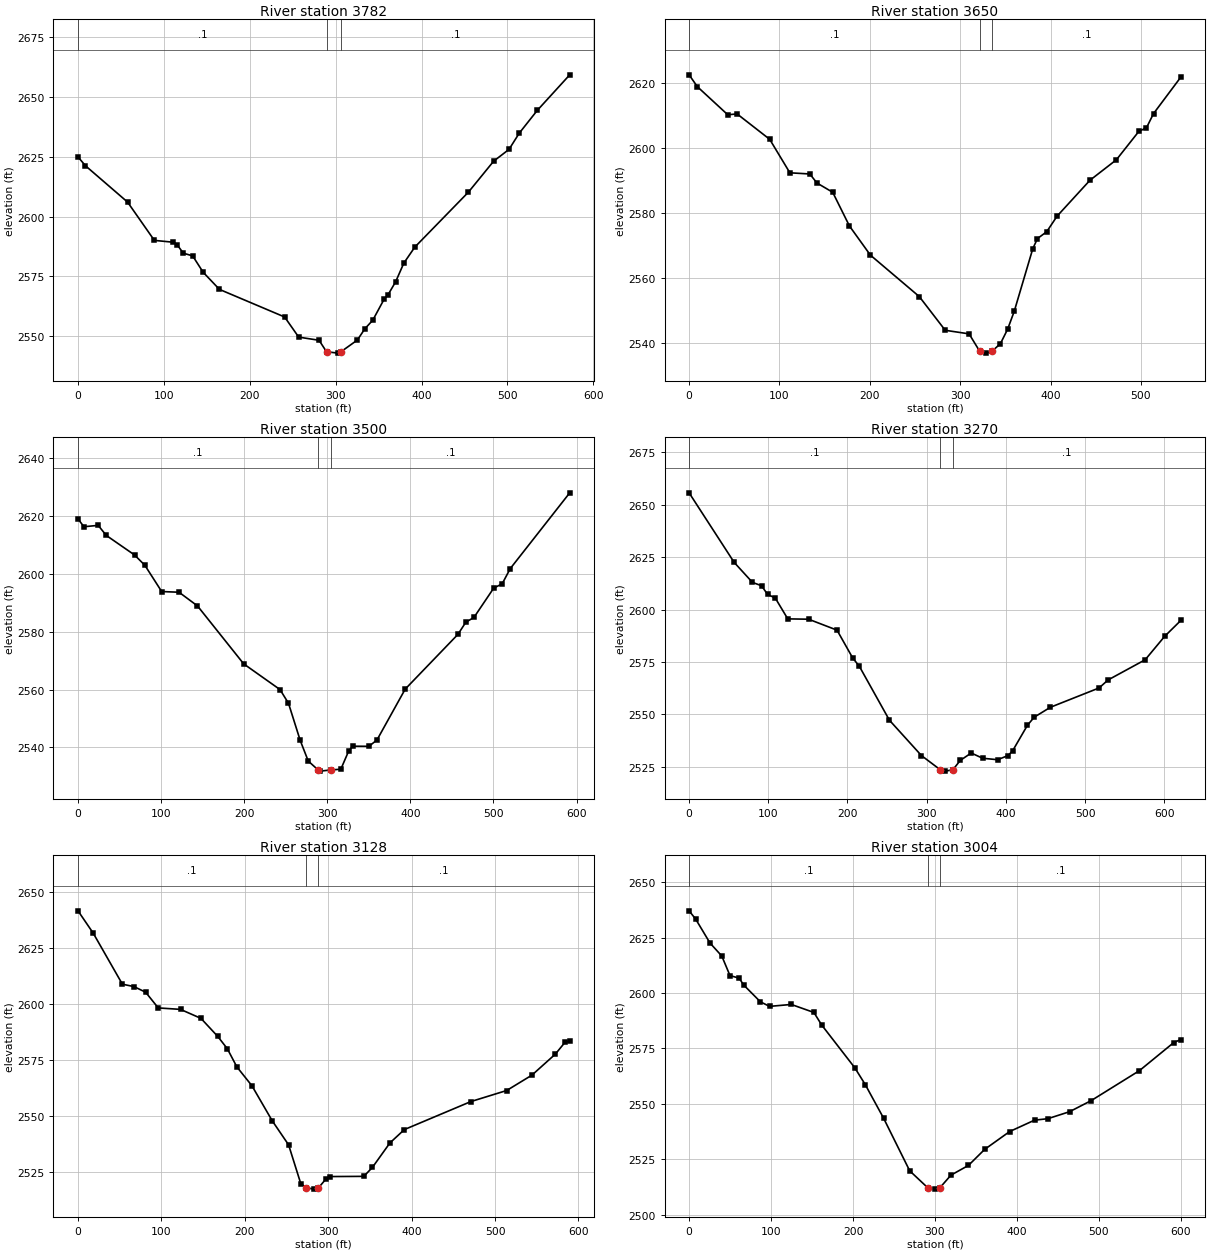
Type RM Length L Ch R = 1 ,3782    ,131.3,132.5,134.1
XS GIS Cut Line= 2
2259144.66679176665249.469496885 2258891.2322891665762.889739814
#Sta/Elev= 30
       0 2624.99     8.6 2621.31    57.7 2606.08    88.9 2590.04   111.2 2589.26
   115.7  2588.1   122.6 2584.68   133.5 2583.56   145.7 2576.71   164.7 2569.52
   240.6 2557.97     257 2549.54   280.7 2548.22  289.392543.412     303 2542.84
  306.192543.412   325.3 2548.32   334.2 2553.12   343.2 2556.59   356.5 2565.45
     361 2567.26   369.9 2572.73   379.4 2580.52   392.2 2587.22   454.7 2610.27
     484  2623.2   501.9 2628.14   513.8 2634.92   534.7 2644.42   572.6 2659.35
#Mann= 3 ,-1,0
       0      .1       0  289.39    .045       0  306.19      .1       0
Bank Sta=289.39,306.19
XS Rating Curve= 0 ,0
Exp/Cntr(USF)=0,0
Exp/Cntr=0.3,0.1

Type RM Length L Ch R = 1 ,3650    ,150.4,149.1,148.9
XS GIS Cut Line= 3
2259063.92431794665180.2835108362258912.93352797665436.785937174
2258758.30440571665628.707965392
#Sta/Elev= 30
       0 2622.52     9.2 2618.85    42.8 2610.21    53.1 2610.47    89.2 2602.64
   111.5 2592.32   133.6 2591.96   141.4 2589.19   158.9 2586.32   177.4 2575.94
   200.6 2566.95   254.7 2554.17   283.4 2543.78   309.8 2542.68  321.332537.409
     329 2536.74   335.52537.409   344.4 2539.62   352.5 2544.14   359.8 2549.66
   380.3 2568.94   385.5 2572.06   395.7 2574.16   407.2 2578.97   443.5 2590.01
   472.8 2596.34   497.6 2605.07   506.1 2606.21   513.9 2610.57   544.1 2621.82
#Mann= 3 ,-1,0
       0      .1       0  321.33    .045       0   335.5      .1       0
Bank Sta=321.33,335.5
XS Rating Curve= 0 ,0
Exp/Cntr(USF)=0,0
Exp/Cntr=0.3,0.1

Type RM Length L Ch R = 1 ,3500    ,225.9,230.1,229.9
XS GIS Cut Line= 2
2258964.18575016665105.1672232012258627.76488354665592.069706765
#Sta/Elev= 30
       0 2619.07     7.1 2616.36    24.3 2616.83      34 2613.36    68.1 2606.57
    80.5    2603   100.7 2593.92   121.6 2593.68   143.8 2588.94   199.4 2568.88
   243.1 2559.98   253.3 2555.25   267.4 2542.39   277.1 2535.23  288.94 2532.16
   291.7 2531.74   304.8 2532.17   316.3 2532.39   325.8 2538.73   330.6 2540.37
   350.1 2540.33   359.8 2542.52   393.8 2560.14   457.2 2579.08   466.8 2583.32
   476.5 2584.94   500.3 2595.11   510.5  2596.6   520.2 2601.86   591.8  2628.1
#Mann= 3 ,-1,0
       0      .1       0  288.94    .045       0   304.8      .1       0
Bank Sta=288.94,304.8
XS Rating Curve= 0 ,0
Exp/Cntr(USF)=0,0
Exp/Cntr=0.3,0.1

Type RM Length L Ch R = 1 ,3270    ,143.2,142.7,140.6
XS GIS Cut Line= 2
2258896.87344729664965.7074751512258449.48281511665396.324097438
#Sta/Elev= 30
       0 2655.73    56.9 2622.53      80 2612.98    91.5 2611.37    99.1 2607.24
   108.8 2605.53   124.6 2595.56   150.9  2595.4   186.8 2590.18   206.6 2576.91
   215.1 2572.85     253 2547.18   293.4 2530.32   317.4 2523.48     323 2522.88
  333.052523.481   342.4 2527.98   356.3 2531.53   370.7 2529.03   389.6 2528.33
     403 2530.34   408.8 2532.72   427.3 2544.78   435.8 2548.62   456.2 2553.35
   517.8 2562.59   529.1  2566.4     576 2576.05   600.6 2587.23     621 2594.81
#Mann= 3 ,-1,0
       0      .1       0   317.4    .045       0  333.05      .1       0
Bank Sta=317.4,333.05
XS Rating Curve= 0 ,0
Exp/Cntr(USF)=0,0
Exp/Cntr=0.3,0.1

Type RM Length L Ch R = 1 ,3128    ,122.5,123.7,124
XS GIS Cut Line= 3
2258742.67891693664846.3834257442258526.56197899665155.004962115
 2258367.7487746665296.627046444
#Sta/Elev= 30
       0 2641.54    18.2  2631.6    53.2  2608.8      67 2607.73    81.1 2605.22
    96.2  2598.2   122.9 2597.55   147.4 2593.54   167.5 2585.51     179 2580.01
   190.5 2571.87   208.5 2563.48   232.9 2547.81   252.5 2537.09   267.1 2519.79
  273.852517.891   283.3 2517.32   288.32517.892   297.2 2521.81   302.5 2522.93
   342.7 2523.02     353 2527.02     374 2537.94   391.3  2543.9   471.1 2556.41
     514 2561.34   544.3 2568.21   572.4  2577.6     584 2582.89   589.6 2583.38
#Mann= 3 ,-1,0
       0      .1       0  273.85    .045       0   288.3      .1       0
Bank Sta=273.85,288.3
XS Rating Curve= 0 ,0
Exp/Cntr(USF)=0,0
Exp/Cntr=0.3,0.1

Type RM Length L Ch R = 1 ,3004    ,172.6,170.1,167
XS GIS Cut Line= 2
2258672.91003896664787.1093076472258278.99908558665239.695388752
#Sta/Elev= 30
       0 2637.15       8 2633.43    25.5 2622.62    39.9 2616.74    49.9  2607.9
    61.1 2606.77    66.4 2603.74      87 2596.07    98.2 2594.01   124.7 2594.88
   152.3 2591.26   161.8 2585.59   202.2 2566.28   214.9 2558.73   237.3 2543.54
   269.2 2519.76  291.232512.106   299.7  2511.5  305.992512.108   319.5 2517.81
   340.9 2522.22   360.6 2529.43   391.1 2537.49   421.5 2542.64   437.6 2543.29
   464.2 2546.45   490.6 2551.46   549.5    2565   591.4 2577.68     600 2579.05
#Mann= 3 ,-1,0
       0      .1       0  291.23    .045       0  305.99      .1       0
Bank Sta=291.23,305.99
XS Rating Curve= 0 ,0
Exp/Cntr(USF)=0,0
Exp/Cntr=0.3,0.1

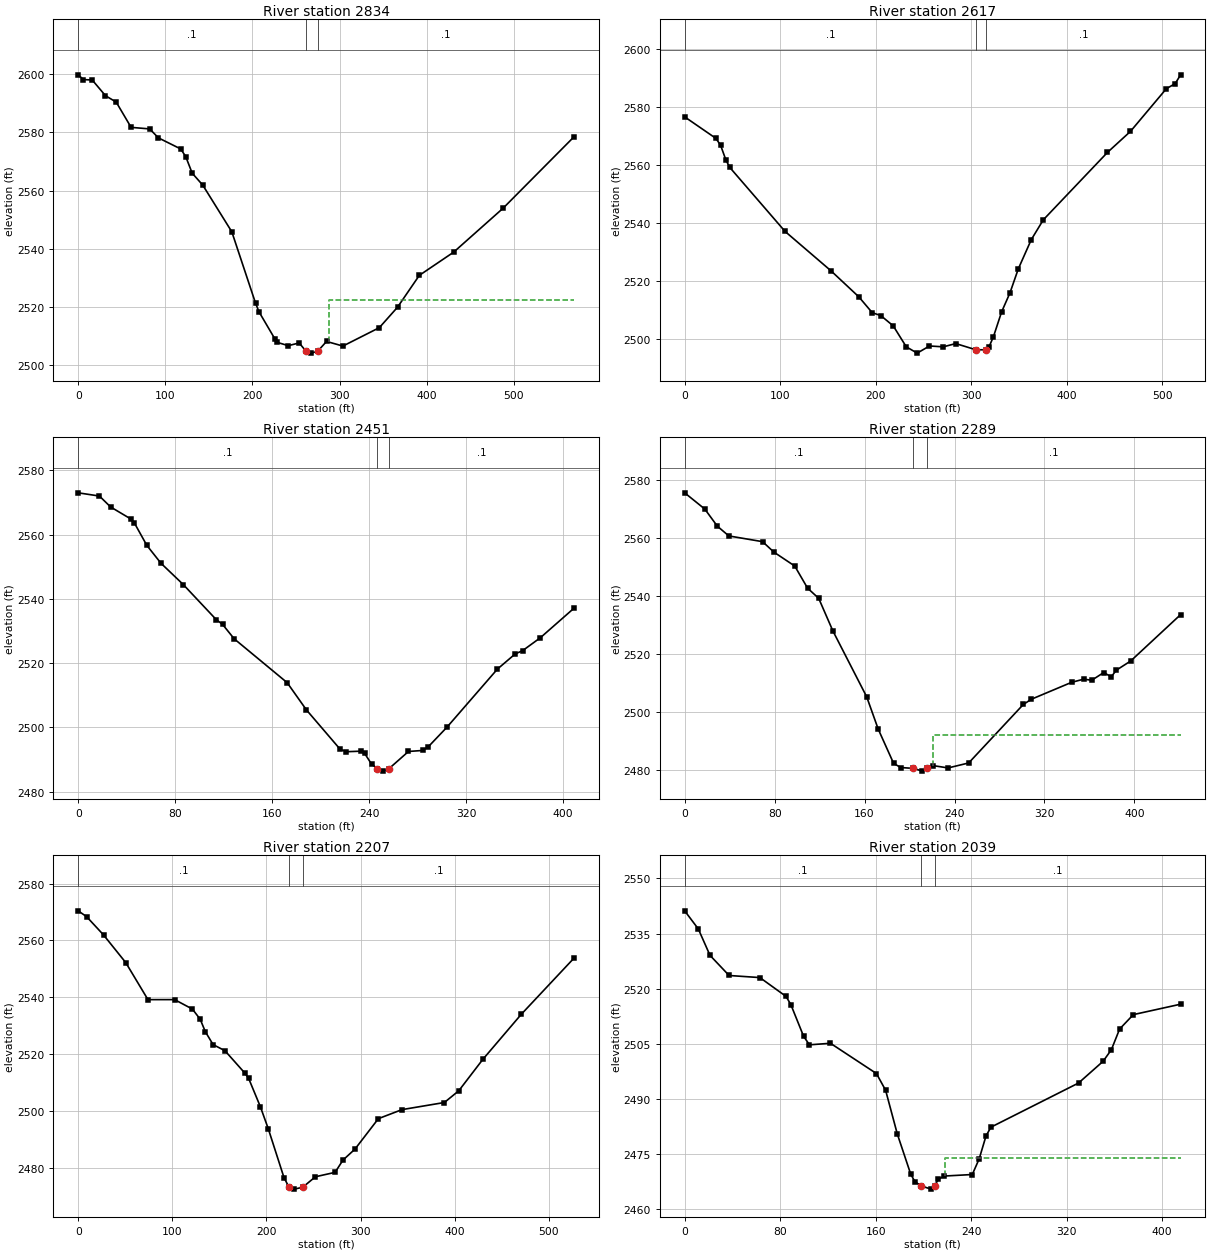
Type RM Length L Ch R = 1 ,2834    ,214.1,216.9,214.7
XS GIS Cut Line= 3
2258476.64875293664692.4700166172258367.27317938664832.548554829
 2258253.8064053665207.190329588
#Sta/Elev= 30
       0 2599.81       6 2598.17    16.1 2598.03    31.3 2592.63    43.6 2590.43
    60.7 2581.74    82.1  2581.2      92 2578.13   117.6 2574.32   123.4 2571.69
   130.8 2565.99     143 2561.85   176.3 2545.81   203.5 2521.28   207.6 2518.23
   225.6 2509.03   228.5 2507.77   241.1 2506.65   253.6 2507.58  261.492504.723
   267.3 2504.08  274.832504.722     285  2508.1   303.8 2506.51   345.6 2512.84
   366.5 2519.88   391.5 2530.83   430.9 2538.81   487.7 2553.94   569.2 2578.54
#Mann= 3 ,-1,0
       0      .1       0  261.49    .045       0  274.83      .1       0
#XS Ineff= 2 , 0
                           288.3         2522.24
Permanent Ineff=
       F       F
Bank Sta=261.49,274.83
XS Rating Curve= 0 ,0
Exp/Cntr(USF)=0,0
Exp/Cntr=0.3,0.1

Type RM Length L Ch R = 1 ,2617    ,160.2,166.1,167
XS GIS Cut Line= 4
2258351.31637069664701.0884290122258193.54504704664807.431320617
2258113.91829964664988.9738726372258049.37669524665102.842940186
#Sta/Elev= 30
       0 2576.53    32.7 2569.11    37.6 2566.74    43.1  2561.7    47.2 2559.09
   105.1 2536.99   153.3 2523.36   182.3 2514.42   196.5  2508.9   205.3 2507.95
   218.4 2504.38   232.1 2497.13   243.5 2494.96   256.4 2497.43   270.8 2497.13
   283.9 2498.26     305 2496.12  315.84 2496.11   318.8 2497.18   323.3 2500.56
   331.9 2509.18   340.7 2515.79   349.4 2524.05     363 2534.15   375.6 2540.99
   442.8 2564.27   466.9 2571.53   504.4 2586.24   513.7 2588.02   519.4 2591.05
#Mann= 3 ,-1,0
       0      .1       0     305    .045       0  315.84      .1       0
Bank Sta=305,315.84
XS Rating Curve= 0 ,0
Exp/Cntr(USF)=0,0
Exp/Cntr=0.3,0.1

Type RM Length L Ch R = 1 ,2451    ,160.8,161.7,160.3
XS GIS Cut Line= 4
2258311.31754597664648.8901243082258133.01444117664751.711950351
2258057.31645395664803.1146346362257999.37063565664898.828596743
#Sta/Elev= 30
       0 2573.02    17.5 2572.02    26.7 2568.63    43.5 2564.86    46.4  2563.6
    56.6 2556.68    68.3  2551.1    86.7 2544.47   113.8  2533.6   119.1 2532.08
   128.7 2527.59   172.4 2513.95   188.3 2505.47   216.1 2493.23   221.3 2492.46
   233.4 2492.63   236.3 2491.95     242 2488.62  246.82 2487.23   251.2 2486.42
  256.54 2487.23   272.5 2492.54   284.2 2492.85     289 2494.06   304.4 2500.15
   345.9 2518.18   360.5 2522.87   366.7 2523.92   381.2 2527.89   409.2 2537.16
#Mann= 3 ,-1,0
       0      .1       0  246.82    .045       0  256.54      .1       0
Bank Sta=246.82,256.54
XS Rating Curve= 0 ,0
Exp/Cntr(USF)=0,0
Exp/Cntr=0.3,0.1

Type RM Length L Ch R = 1 ,2289    ,86.5,82.2,77.6
XS GIS Cut Line= 4
 2258201.5844576 664513.54911996 2258042.3558781664633.188079974
2258014.51262922664651.8952628122257897.91902455664824.610415996
#Sta/Elev= 30
       0 2575.44    17.9 2569.85    29.1 2563.94    39.3  2560.6    69.3 2558.63
    79.3 2555.05    97.9 2550.24   109.3 2542.63   119.2 2539.13   131.8 2527.92
   161.9 2505.22   172.1 2494.14   185.8 2482.34   192.1 2480.89  203.512480.589
   211.4 2479.65  215.382480.588   220.9 2481.55   234.3 2480.75   252.6 2482.46
   301.2  2502.6   308.4  2504.4   344.1 2510.21   354.9  2511.3   362.1 2510.94
   372.7 2513.58   379.4 2512.11   383.9 2514.39   396.7 2517.56   441.1 2533.52
#Mann= 3 ,-1,0
       0      .1       0  203.51    .045       0  215.38      .1       0
#XS Ineff= 2 , 0
                          221.17         2491.99
Permanent Ineff=
       F       F
Bank Sta=203.51,215.38
XS Rating Curve= 0 ,0
Exp/Cntr(USF)=0,0
Exp/Cntr=0.3,0.1

Type RM Length L Ch R = 1 ,2207    ,165.3,167.9,169.9
XS GIS Cut Line= 4
2258068.95972533664386.3724507482257999.38312906664497.464091269
 2257929.4128494664727.5586325132257832.57745298664849.032277556
#Sta/Elev= 30
       0 2570.39       9 2568.31    26.9 2561.91    50.5 2552.18    74.1 2539.15
   102.4 2539.16   121.3 2535.83   129.6 2532.25     135 2527.91   143.3 2523.33
   155.9 2521.18   176.8 2513.39     181  2511.5   193.5  2501.5   201.9 2493.76
   218.6 2476.57  223.952473.153   229.6 2472.49  238.552473.153     252 2476.84
   272.9 2478.39   281.3 2482.71   294.1 2486.59   318.9 2497.28     344 2500.46
     389 2502.96   404.3 2507.08   429.9 2518.14   470.8 2534.02   526.9 2553.81
#Mann= 3 ,-1,0
       0      .1       0  223.95    .045       0  238.55      .1       0
Bank Sta=223.95,238.55
XS Rating Curve= 0 ,0
Exp/Cntr(USF)=0,0
Exp/Cntr=0.3,0.1

Type RM Length L Ch R = 1 ,2039    ,161.3,163,160.9
XS GIS Cut Line= 2
 2257950.7700921664335.8787416612257710.62806593664674.847732308
#Sta/Elev= 30
       0 2541.18    11.4 2536.25    21.2 2529.05    37.2 2523.56      63 2522.99
    84.9 2517.86    88.9 2515.65    99.6    2507   104.5 2504.67   122.1 2505.09
   160.6 2496.85   168.3 2492.29   178.1 2480.37   189.3 2469.46   192.8  2467.4
  198.032466.207   206.5 2465.35  209.342466.206   212.4 2468.03   217.3 2468.91
   240.9 2469.33   246.7 2473.62   252.4 2479.84   256.5 2482.23   329.9 2494.26
   350.5 2500.19   357.4 2503.34   364.3 2508.97   375.8  2512.9   415.4 2515.74
#Mann= 3 ,-1,0
       0      .1       0  198.03    .045       0  209.34      .1       0
#XS Ineff= 2 , 0
                          217.92         2473.83
Permanent Ineff=
       F       F
Bank Sta=198.03,209.34
XS Rating Curve= 0 ,0
Exp/Cntr(USF)=0,0
Exp/Cntr=0.3,0.1

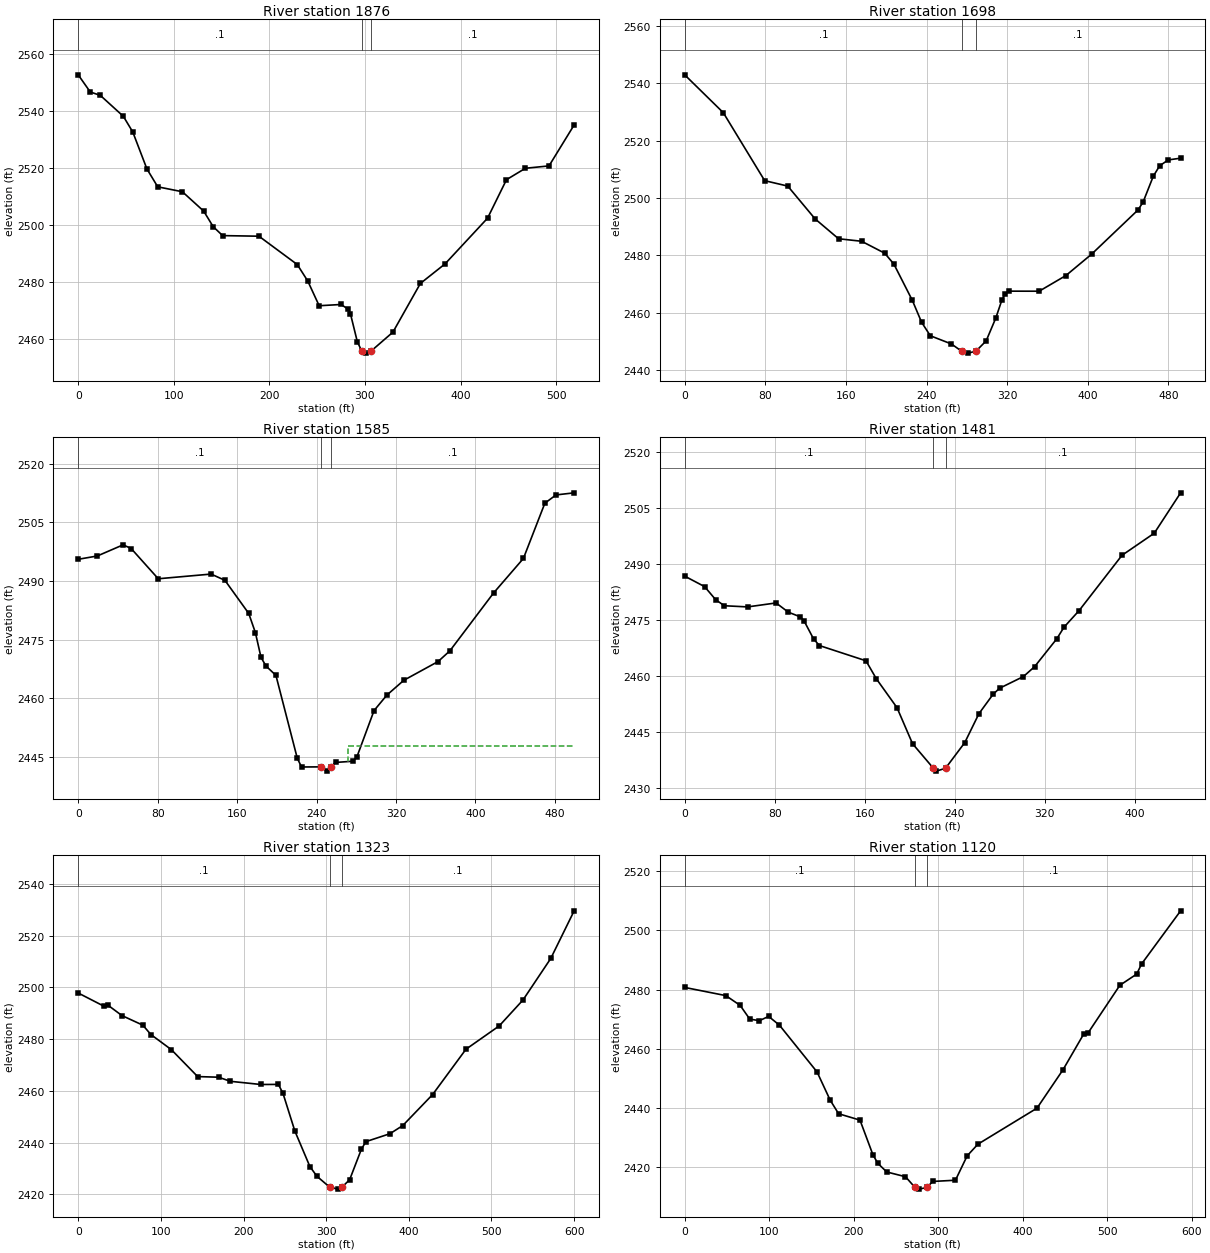
Type RM Length L Ch R = 1 ,1876    ,174.7,178.2,180.1
XS GIS Cut Line= 2
2257878.25308826664231.031325747 2257572.6745531664650.456100722
#Sta/Elev= 30
       0 2552.84    12.6 2546.81    23.1 2545.63    47.2 2538.27    57.1 2532.75
    71.9 2519.76    83.2 2513.49     109 2511.76   131.3 2504.95   141.2  2499.5
   151.1 2496.35   189.1 2496.14   229.2 2486.18   240.2 2480.38   252.1 2471.71
     275 2472.15     282  2470.6   284.8 2468.94     292 2459.11  296.532455.853
   300.8 2455.06  306.672455.853   329.3 2462.44     358 2479.54   383.8 2486.41
   428.3 2502.48   448.1    2516   467.9 2520.01   492.6 2520.84   518.9 2535.24
#Mann= 3 ,-1,0
       0      .1       0  296.53    .045       0  306.67      .1       0
Bank Sta=296.53,306.67
XS Rating Curve= 0 ,0
Exp/Cntr(USF)=0,0
Exp/Cntr=0.3,0.1

Type RM Length L Ch R = 1 ,1698    ,116.5,112.4,109.1
XS GIS Cut Line= 3
 2257825.5456877664210.4859932142257549.17891345664364.519654781
2257440.18944971664502.508601147
#Sta/Elev= 30
       0    2543    38.3  2529.8    79.4 2506.06   102.3 2504.17   129.4 2492.73
   152.7 2485.79   175.6 2484.91   198.5 2480.75   207.6 2476.96     226 2464.24
   235.1 2456.66   243.8 2451.93   264.7 2449.07  275.062446.499   280.9 2445.87
  288.912446.499   299.2 2450.14   308.8 2458.14   314.7 2464.29     318 2466.53
   322.3  2467.5   351.8 2467.48   378.4 2472.96   403.9 2480.42   449.8  2495.8
   454.9 2498.54   465.1 2507.63   471.4 2511.25   479.9  2513.3   492.2 2513.91
#Mann= 3 ,-1,0
       0      .1       0  275.06    .045       0  288.91      .1       0
Bank Sta=275.06,288.91
XS Rating Curve= 0 ,0
Exp/Cntr(USF)=0,0
Exp/Cntr=0.3,0.1

Type RM Length L Ch R = 1 ,1585    ,104.9,104.7,104.4
XS GIS Cut Line= 3
 2257652.7612297664066.7278526552257527.77326299664219.823664131
2257417.51155748664500.704416928
#Sta/Elev= 30
       0 2495.57    19.2 2496.41    45.2 2499.27    53.3 2498.33    80.6 2490.58
   133.8 2491.78   147.7 2490.19   171.7  2481.7   178.4 2476.79   184.1 2470.42
   189.1 2468.23   199.1 2465.83   220.6  2444.6   224.9 2442.37  244.49  2442.4
   250.7 2441.31  254.162442.395   259.3 2443.54   276.4 2443.84   280.7    2445
   297.9 2456.82   310.8 2460.78   327.9 2464.58   362.4 2469.38   374.3 2472.13
   418.2 2486.92   448.3 2495.78   469.9 2509.93   481.1 2512.05   499.4 2512.59
#Mann= 3 ,-1,0
       0      .1       0  244.49    .045       0  254.16      .1       0
#XS Ineff= 2 , 0
                          271.99         2447.64
Permanent Ineff=
       F       F
Bank Sta=244.49,254.16
XS Rating Curve= 0 ,0
Exp/Cntr(USF)=0,0
Exp/Cntr=0.3,0.1

Type RM Length L Ch R = 1 ,1481    ,153.9,157.8,159.4
XS GIS Cut Line= 4
2257516.34548179664041.1737558942257415.80829566664217.827423643
2257397.41347927664273.9633288342257292.38221875 664418.09260149
#Sta/Elev= 30
       0 2486.67    17.7 2483.86    27.6 2480.34    35.3 2478.74    55.9 2478.43
    81.2 2479.49    92.1 2477.02   102.8 2475.76   105.9 2474.79   114.5 2469.88
   119.7 2468.09   161.1 2464.01   170.3  2459.2   188.7 2451.45   202.5 2441.81
  220.982435.259   223.6 2434.48  231.822435.257   248.9 2442.12   261.5 2449.87
   274.1 2455.06   279.8 2456.66     301 2459.79   310.9 2462.42   330.7 2469.91
   337.1 2473.01   350.5 2477.45   388.6 2492.24   417.3 2498.16   440.7 2508.96
#Mann= 3 ,-1,0
       0      .1       0  220.98    .045       0  231.82      .1       0
Bank Sta=220.98,231.82
XS Rating Curve= 0 ,0
Exp/Cntr(USF)=0,0
Exp/Cntr=0.3,0.1

Type RM Length L Ch R = 1 ,1323    ,205.5,202.7,201.9
XS GIS Cut Line= 2
2257506.57904185663919.2211254062257089.08358053664350.147499375
#Sta/Elev= 30
       0 2497.86    30.6 2492.84    36.1 2493.12    52.9 2489.13    78.2 2485.41
    87.9  2481.8   112.7 2475.94   144.5 2465.52   169.8 2465.28   184.1 2463.69
   220.9 2462.46   242.2 2462.49   247.8 2458.98   262.1 2444.45   280.3  2430.7
   288.8 2426.94  304.282422.731   313.9 2421.97   319.1 2422.73   328.4 2425.62
   342.5 2437.34     348 2440.34   377.1 2443.41   392.6 2446.55   428.8 2458.58
   469.1  2476.1   509.3 2485.12   538.1 2495.16   571.7 2511.23     600 2529.66
#Mann= 3 ,-1,0
       0      .1       0  304.28    .045       0   319.1      .1       0
Bank Sta=304.28,319.1
XS Rating Curve= 0 ,0
Exp/Cntr(USF)=0,0
Exp/Cntr=0.3,0.1

Type RM Length L Ch R = 1 ,1120    ,139.8,143.9,145.3
XS GIS Cut Line= 4
2257370.06846999663782.7512601712257209.07226622663912.821639484
 2257138.1247866664046.5303510862256989.86274584 664220.26071786
#Sta/Elev= 30
       0 2480.72    48.7 2477.95    65.6 2474.65      77    2470    88.4 2469.47
    99.3 2470.92   112.1 2467.95   156.6 2452.12   172.1 2442.59   182.1 2437.98
   207.4 2435.82   222.7 2424.09   228.6 2421.16   239.1 2418.27   261.2 2416.67
  272.522413.025   277.2 2412.47  286.522413.023   293.4 2415.07   320.3 2415.48
   334.2 2423.74   346.9 2427.68   416.8 2439.87   447.6 2452.88   472.2 2465.02
   477.5 2465.45   514.8 2481.44   534.7 2485.23   540.6  2488.7   586.7 2506.64
#Mann= 3 ,-1,0
       0      .1       0  272.52    .045       0  286.52      .1       0
Bank Sta=272.52,286.52
XS Rating Curve= 0 ,0
Exp/Cntr(USF)=0,0
Exp/Cntr=0.3,0.1