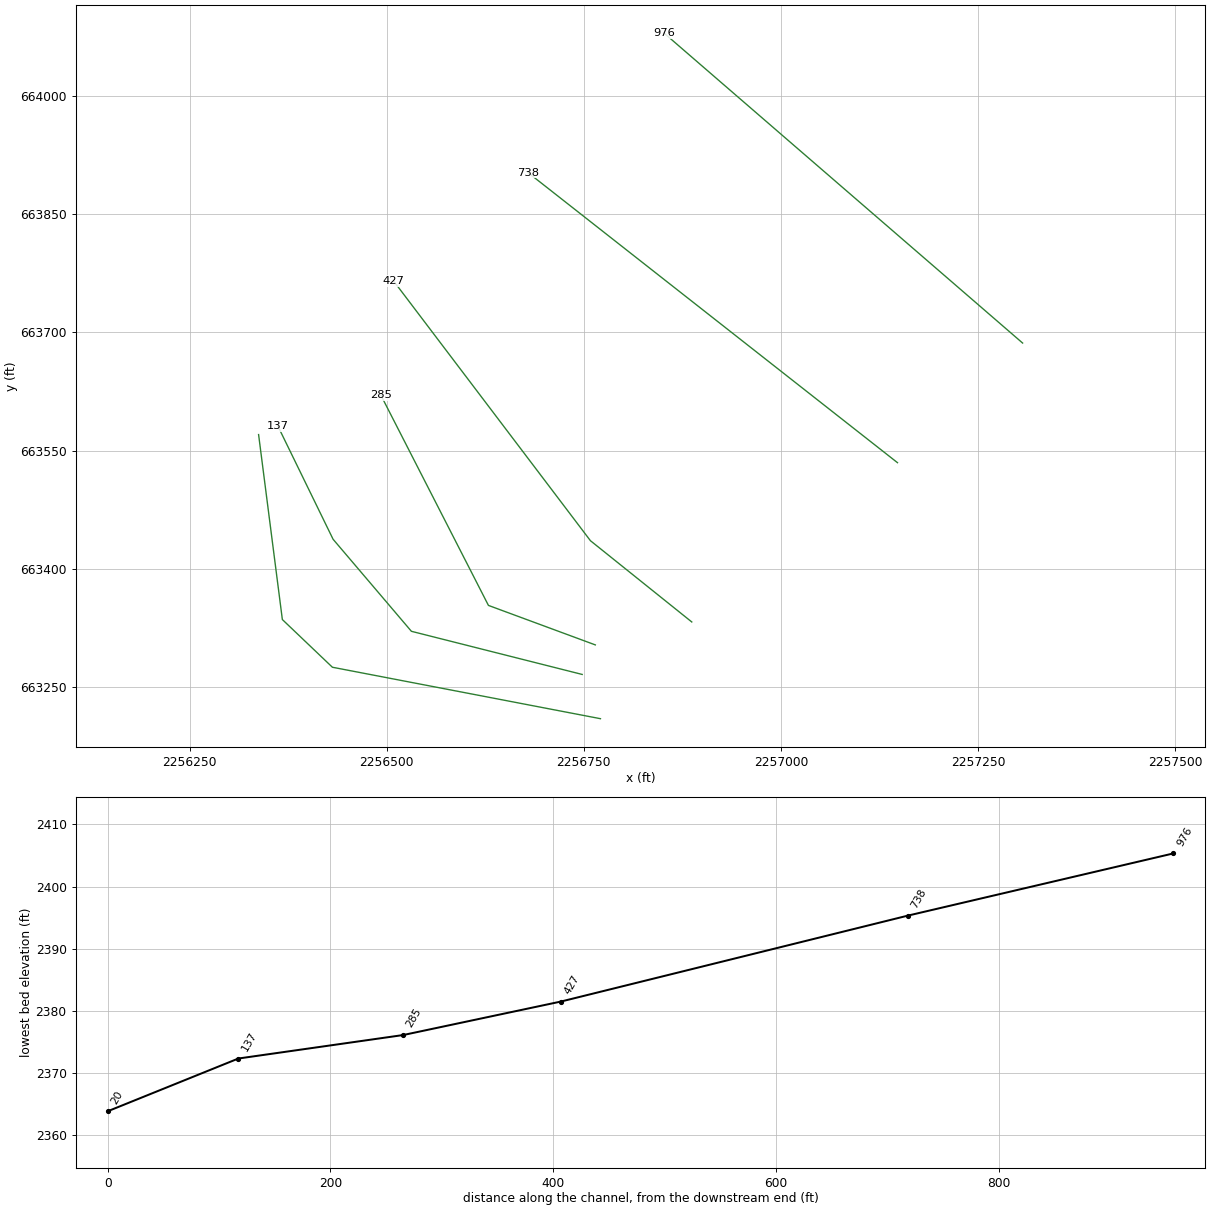
HEC-RAS study PNTHRNT1_1.prj: PNTHRNT1_1

--- PNTHRNT1_1.g01 (geometry) --- (continued)

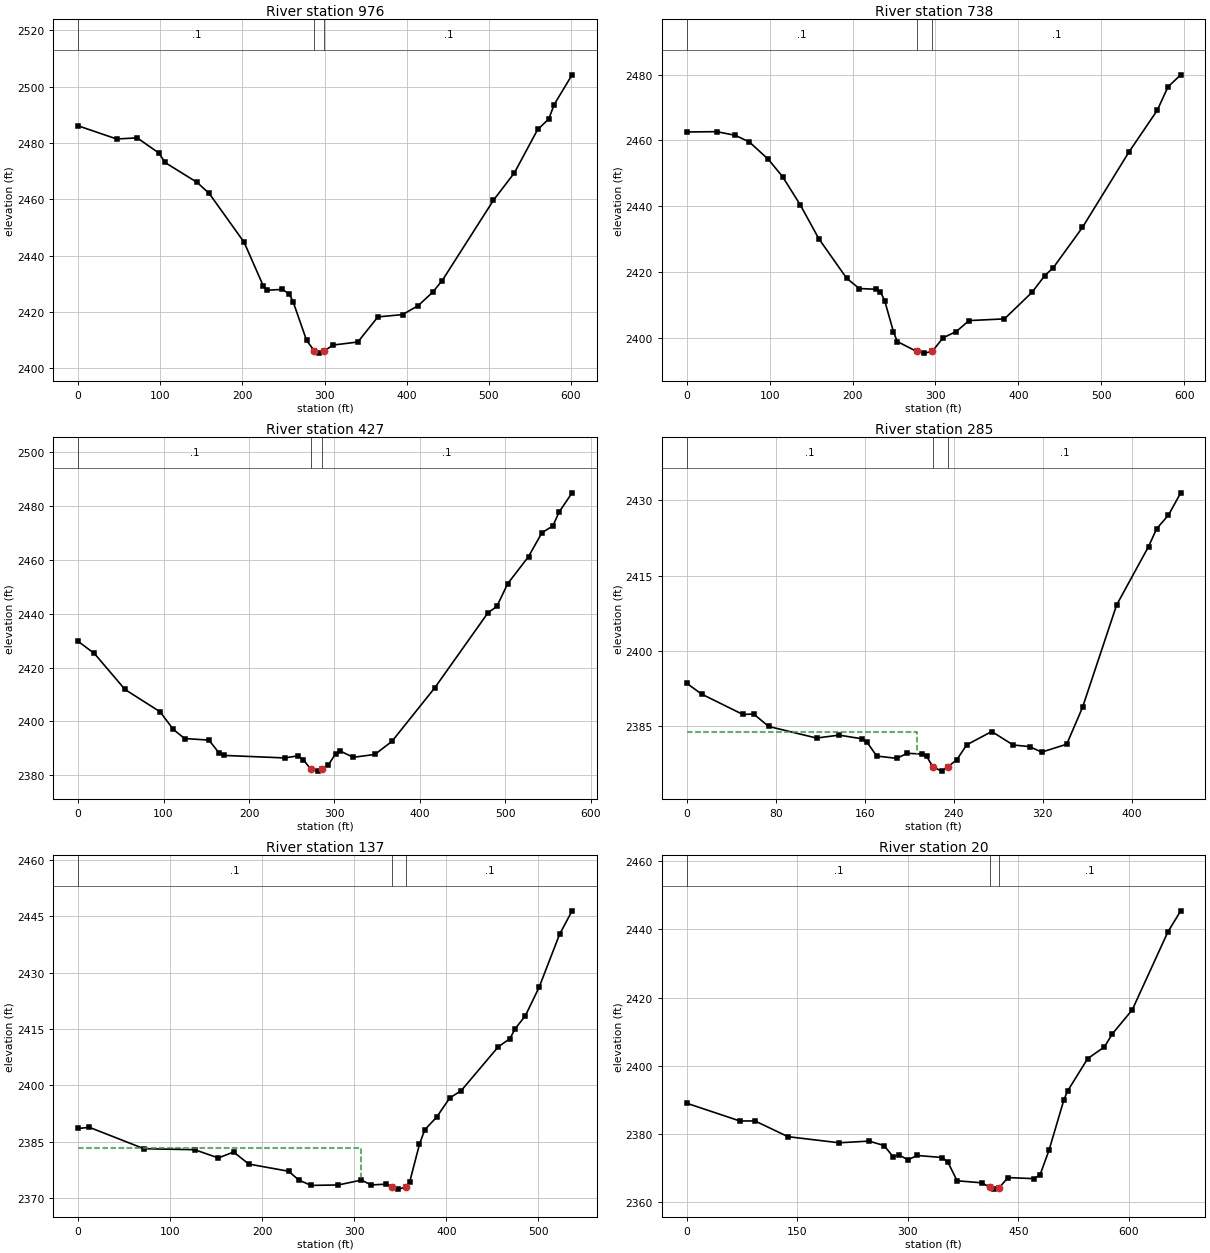
Type RM Length L Ch R = 1 ,976     ,237.6,238.3,239.1
XS GIS Cut Line= 2
2257306.59608932663686.5331573722256851.70710908664079.760021705
#Sta/Elev= 30
       0 2486.05    46.9 2481.37    71.9 2481.77    98.4 2476.37   105.7 2473.04
   144.7 2465.99   159.6 2462.03   202.1 2444.68   225.3 2429.27   230.5  2427.7
   248.7 2427.95     257 2426.34   261.7 2423.59   278.1 2409.87  287.662406.094
   292.9 2405.34  299.862406.096   309.9 2408.19   340.5 2409.29   364.9  2418.2
   394.9 2419.02   413.9 2422.19   431.5 2426.94   443.2  2431.1   505.5 2459.59
   531.1 2469.36   559.4 2484.74   572.9 2488.46   579.5  2493.6   601.3 2504.15
#Mann= 3 ,-1,0
       0      .1       0  287.66    .045       0  299.86      .1       0
Bank Sta=287.66,299.86
XS Rating Curve= 0 ,0
Exp/Cntr(USF)=0,0
Exp/Cntr=0.3,0.1

Type RM Length L Ch R = 1 ,738     ,312.7,311.6,308.1
XS GIS Cut Line= 2
2257147.89563013663534.7970397942256679.23148614663902.743092316
#Sta/Elev= 30
       0 2462.55    36.2 2462.64    58.5 2461.54    75.6 2459.49    98.4 2454.23
   115.5    2449     137 2440.36   159.3  2430.1   192.9 2418.08   208.1 2414.97
   228.5 2414.73   233.6 2413.93   238.7 2411.31   249.3 2401.83   253.9 2398.85
  277.162395.866   286.4 2395.33  296.082395.866   309.2 2399.99   325.1  2401.9
   340.5 2405.22   383.2 2405.74   416.7 2413.88   431.7 2418.86   442.1 2421.29
   477.3 2433.55   533.6 2456.56   567.4 2469.09   580.4 2476.25   595.8 2479.92
#Mann= 3 ,-1,0
       0      .1       0  277.16    .045       0  296.08      .1       0
Bank Sta=277.16,296.08
XS Rating Curve= 0 ,0
Exp/Cntr(USF)=0,0
Exp/Cntr=0.3,0.1

Type RM Length L Ch R = 1 ,427     ,143.4,141.8,141.1
XS GIS Cut Line= 3
2256886.97280992663332.7691394082256758.44316998663435.823141153
2256508.79269753663765.227630257
#Sta/Elev= 30
       0 2429.75      19 2425.24    54.9 2411.85    95.9 2403.56   111.3 2397.03
   124.6 2393.61   153.1 2393.03   164.5 2388.41   170.2 2387.34   241.6  2386.4
   256.8 2387.14   263.7 2385.72  272.272382.187   281.1 2381.49  285.132382.187
     293 2383.86   301.5 2388.04     307 2388.92     322 2386.63   347.2 2387.69
   367.2 2392.53   417.4 2412.47   479.7 2440.38     490 2442.72   502.7 2451.16
   527.1 2461.27   542.9 2470.18   555.6 2472.66   562.9 2477.82   578.1 2484.98
#Mann= 3 ,-1,0
       0      .1       0  272.27    .045       0  285.13      .1       0
Bank Sta=272.27,285.13
XS Rating Curve= 0 ,0
Exp/Cntr(USF)=0,0
Exp/Cntr=0.3,0.1

Type RM Length L Ch R = 1 ,285     ,146.2,148,151
XS GIS Cut Line= 3
2256764.61562774663303.6777174822256629.06356387663353.763283484
2256492.57928254663620.514366878
#Sta/Elev= 30
       0 2393.57    13.3 2391.42    50.5 2387.36    60.2 2387.45    73.6 2384.98
   116.7 2382.67   136.9 2383.25   157.3 2382.53   161.8 2381.92   170.8 2379.09
   188.8 2378.63   198.2 2379.63   211.3  2379.5   215.7 2379.03   221.22376.939
   229.2 2376.09  234.692376.938   242.8 2378.36   251.7 2381.32   274.2 2383.97
   293.4 2381.29   308.2 2380.97   319.1 2379.87   341.6 2381.44   355.8 2388.76
   386.5 2409.15   415.2 2420.77   422.4 2424.29   433.1 2427.03   444.1 2431.45
#Mann= 3 ,-1,0
       0      .1       0   221.2    .045       0  234.69      .1       0
#XS Ineff= 2 , 0
          206.61 2383.87
Permanent Ineff=
       F       F
Bank Sta=221.2,234.69
XS Rating Curve= 0 ,0
Exp/Cntr(USF)=0,0
Exp/Cntr=0.3,0.1

Type RM Length L Ch R = 1 ,137     ,116.1,117.3,118.2
XS GIS Cut Line= 4
2256747.97694427663266.2009597472256531.35227238663320.919989077
 2256431.9995746663437.6979707922256361.91289657663581.395238038
#Sta/Elev= 30
       0 2388.47    12.2 2388.78    71.5 2383.08   126.5 2382.82   152.4 2380.62
   168.9  2382.2   185.4 2378.99   228.7 2377.07   239.5 2374.77     253  2373.3
   282.6 2373.42   307.8 2374.72   318.3 2373.43   334.1 2373.62  341.312372.888
   347.9 2372.31  356.722372.888   360.3 2374.34   370.8 2384.25   376.5 2388.12
   389.5 2391.51   403.7 2396.59   416.2 2398.57   456.3  2410.2     469 2412.41
   474.9  2415.1   485.8 2418.49   500.8 2426.11     523  2440.2   536.6 2446.47
#Mann= 3 ,-1,0
       0      .1       0  341.31    .045       0  356.72      .1       0
#XS Ineff= 2 , 0
          307.63 2383.27
Permanent Ineff=
       F       F
Bank Sta=341.31,356.72
XS Rating Curve= 0 ,0
Exp/Cntr(USF)=0,0
Exp/Cntr=0.3,0.1

Type RM Length L Ch R = 1 ,20      ,,,
XS GIS Cut Line= 4
2256771.12886734663210.0903349952256431.14802136663275.337348306
2256367.67620109663335.8360981892256337.53411101663570.459287295
#Sta/Elev= 30
       0 2389.01    72.2  2383.8    92.6 2383.82   137.4  2379.2   206.8 2377.41
   247.4  2377.9   267.8 2376.61     280 2373.33   288.1 2373.83   300.3 2372.42
   312.7 2373.69   346.8 2373.09   354.7 2371.63   366.9 2366.27   400.5 2365.67
   411.8  2364.3   416.6 2363.82   424.2 2364.29     436 2367.21   471.5 2366.89
   479.6 2368.07   491.7 2375.26   511.8 2389.97   516.8 2392.58   544.1 2402.09
   566.9 2405.54   577.6 2409.36   604.6 2416.39     653 2439.26   670.4 2445.44
#Mann= 3 ,0,0
       0      .1       0   411.8    .045       0   424.2      .1       0
Bank Sta=411.8,424.2
XS Rating Curve= 0 ,0
Exp/Cntr(USF)=0,0
Exp/Cntr=0.3,0.1
LCMann Table=0

Chan Stop Cuts=-1
Use User Specified Reach Order=0
Composite Channel Slope=5